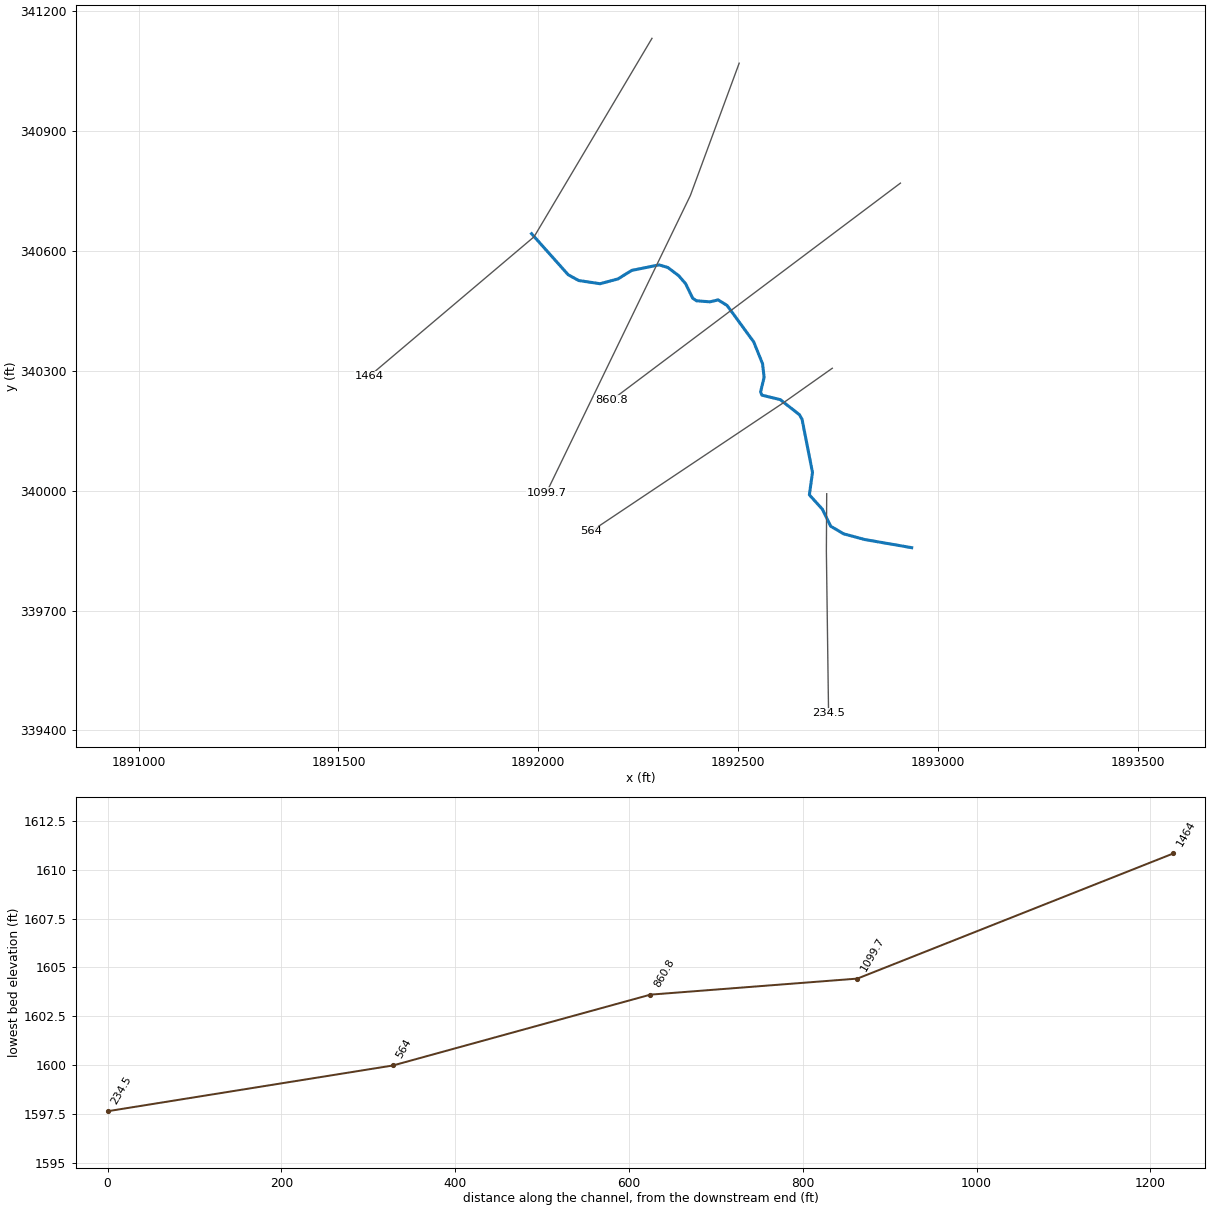
--- TownCrk.prj (project) ---

Proj Title=TownCrk
Current Plan=p01
Default Exp/Contr=0,0
English Units
Geom File=g01
Flow File=f01
Plan File=p01
BEGIN DESCRIPTION:
END DESCRIPTION:
DSS Export Rating Curves= 0
DSS Export Rating Curve Sorted= 0
DSS Export Volume Flow Curves= 0
DXF OffsetX= 0
DXF OffsetY= 0
DXF ScaleX= 0
DXF ScaleY= 0

--- TownCrk.p01 (plan) ---

Plan Title=Floodplain
Program Version=4.00
Geom File=g01
Flow File=f01
K Sum by GR=0
Std Step Tol=0.01
Critical Tol=0.01
Num of Std Step Trials=20
Max Error Tol=0.3
Flow Tol Ratio=0.001
Split Flow NTrial=30
Split Flow Tol=0.02
Split Flow Ratio=0.02
Log Output Level=0
Friction Slope Method=1
Unsteady Friction Slope Method=2
Unsteady Bridges Friction Slope Method=1
Global Log Level=0
CheckData=False
Run HTab=0
Run UNet=0
Run PostProcess=0
UNET Theta=0
UNET Theta Warmup=0
UNET ZTol=0
UNET ZSATol=0
UNET MxIter=0
UNET MaxInSteps=0
UNET DtIC=0
UNET DtMin=0
UNET MaxCRTS=0
UNET WFStab=0
UNET SFStab=0
UNET WFX=0
UNET SFX=0
UNET DSS MLevel=0
UNET DZMax Abort=0
UNET Convert EG Bridges=0
UNET Use Existing IB Tables=0
UNET Froude Limit=0
UNET Froude Power=0
Write IC File=0
Echo Input=False
Echo Output=False
Write Detailed=0

--- TownCrk.f01 (steady flow) ---

Flow Title=NFF Regression Equation
Program Version=4.00
Number of Profiles=1
Profile Names=P100yr
River Rch & RM=TownCrk,Main      ,1464
894.6682
River Rch & RM=TownCrk,Main      ,234.5
903.6022
Boundary for River Rch & Prof#=TownCrk,Main      ,1
Up Type=0
Dn Type=3
Dn Slope=0.007575

--- TownCrk.g01 (geometry) ---

Geom Title=USGS 3m DEM
Program Version=4.10

River Reach=TownCrk         ,Main
Reach XY= 30
     1891983.124      340643.119     1892074.827       340540.33
      1892101.14      340525.847      1892154.59      340517.855
      1892199.27      340529.838     1892233.843      340551.151
     1892302.135      340564.994      1892324.27      340558.484
     1892351.614      340537.651     1892368.541      340518.119
     1892386.362      340481.817     1892395.885       340475.15
     1892429.739      340472.546     1892450.062      340477.399
      1892472.57      340463.357     1892539.114      340372.286
     1892561.249      340317.599     1892565.156      340283.744
     1892556.308      340246.852     1892559.523      340239.021
      1892605.52      340227.755     1892653.697      340189.994
     1892660.215      340178.144     1892686.249      340045.463
     1892678.437      339989.474     1892710.832      339953.674
     1892731.838      339910.885     1892764.374      339891.817
      1892817.76      339877.495     1892934.485      339857.299

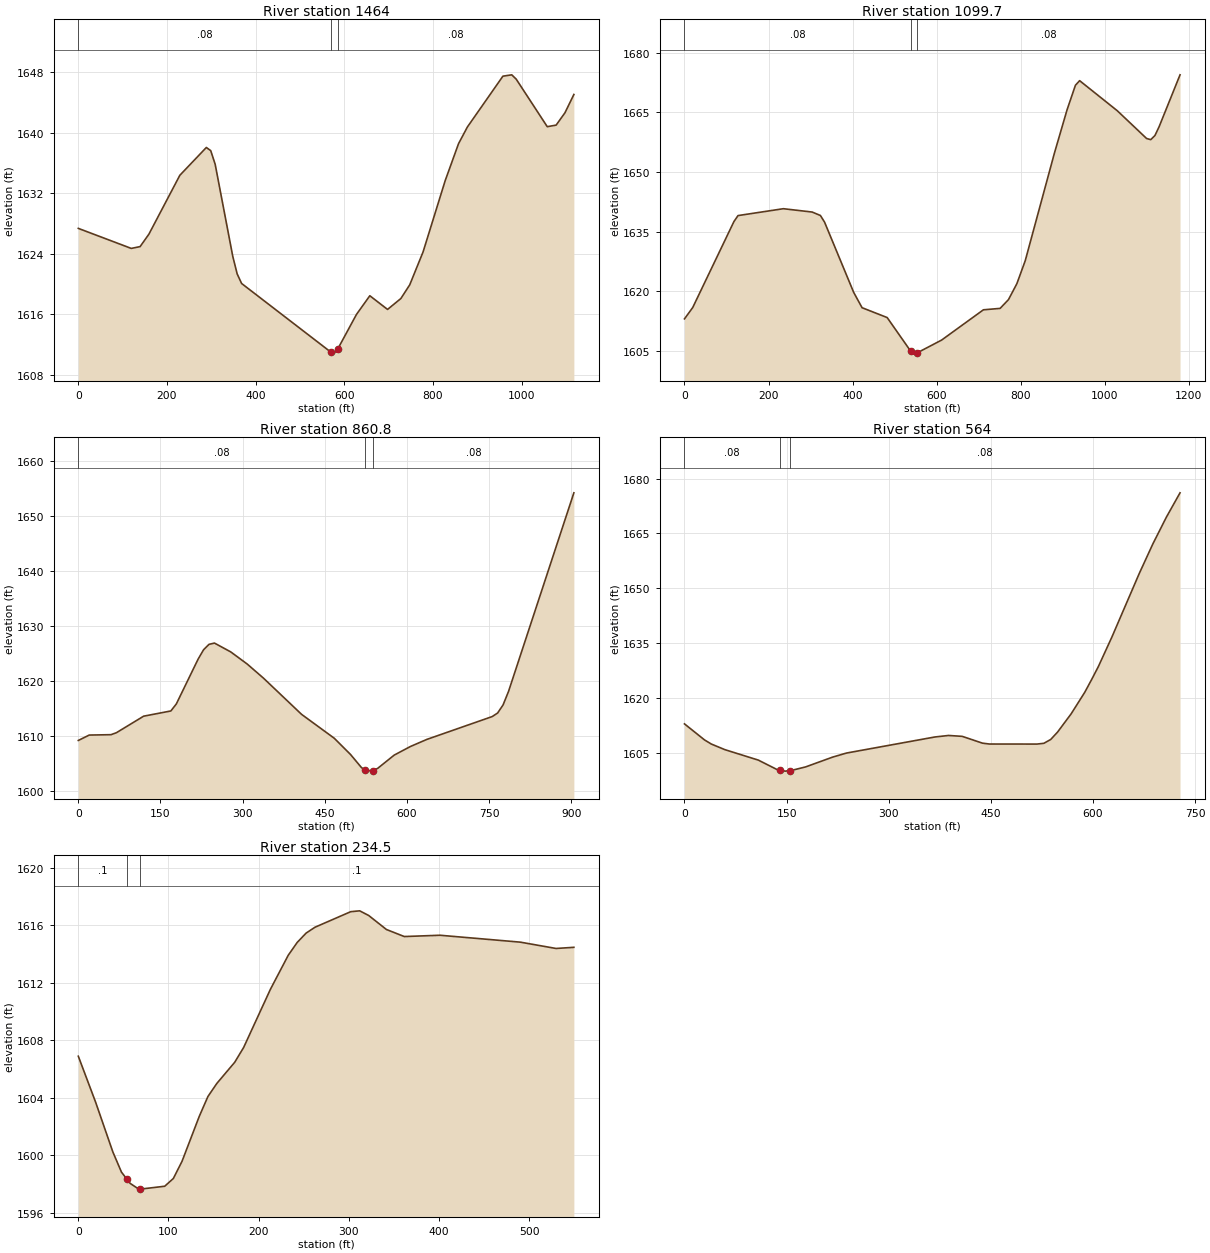
Type RM Length L Ch R = 1 ,1464    ,362.4,363.7,371.4
XS GIS Cut Line= 3
     1892284.542      341131.973     1891989.584      340635.485
     1891577.016      340286.393
#Sta/Elev= 30
       0 1627.33   119.5 1624.68   139.4 1624.92   159.3 1626.57     229 1634.35
   288.8 1638.03   298.7 1637.61   308.7 1635.82   348.5 1623.61   358.4  1621.3
   368.4 1620.04     570 1610.95   577.5 1610.83     585 1611.35   627.5 1615.95
   657.6 1618.42   697.6 1616.61   727.6 1618.05   747.6 1619.86   777.7 1624.21
   827.7 1633.66   857.7 1638.53   877.7 1640.74   957.8 1647.46   977.8 1647.64
   987.8 1647.07  1057.9 1640.78  1077.9 1640.99  1097.9 1642.63  1117.9 1645.04
#Mann= 3 , 0 , 0
       0     .08       0     570    .045       0     585     .08       0
Bank Sta=570,585
XS Rating Curve= 0 ,0
Exp/Cntr=0.3,0.1

Type RM Length L Ch R = 1 ,1099.7  ,248.9,238.1,228.6
XS GIS Cut Line= 3
     1892502.758       341069.78     1892380.603      340738.676
     1892020.413      339995.014
#Sta/Elev= 30
       0 1613.05    19.6  1615.9   117.6 1637.52   127.4 1639.04   235.3 1640.77
   303.9 1639.93   323.5 1639.06   333.3  1637.4   402.7  1619.7   422.6 1615.86
   482.3 1613.38   538.4  1604.9     552 1604.43   553.4 1604.48   611.8 1607.71
   711.3 1615.33   751.1 1615.69     771  1617.9     791 1621.92   810.9 1627.71
   880.6 1654.88   910.4 1665.67   930.3 1671.84   940.3 1672.99  1029.9 1665.42
  1099.6 1658.44  1109.5 1658.15  1119.5 1659.19  1129.4  1661.4  1179.2 1674.46
#Mann= 3 , 0 , 0
       0     .08       0   538.4    .045       0   553.4     .08       0
Bank Sta=538.4,553.4
XS Rating Curve= 0 ,0
Exp/Cntr=0.3,0.1

Type RM Length L Ch R = 1 ,860.8   ,292.2,296.2,295.2
XS GIS Cut Line= 2
     1892906.292      340769.633     1892182.904      340225.947
#Sta/Elev= 30
       0 1609.18    19.9 1610.16    59.7 1610.23    69.6 1610.59   119.3 1613.59
     169 1614.54     179 1615.82   218.8 1623.96   228.7 1625.65   238.7 1626.64
   248.6 1626.87   278.4 1625.26   308.3 1623.07   338.1  1620.5   407.7 1613.92
   467.4 1609.58   497.2 1606.62   517.1 1604.25     524 1603.83     537 1603.61
     539 1603.72   546.9 1604.13   576.8 1606.52   606.6 1608.09   636.4 1609.37
   755.8 1613.52   765.7 1614.17   775.6 1615.63   785.6 1618.09   904.9 1654.16
#Mann= 3 , 0 , 0
       0     .08       0     524    .045       0     539     .08       0
Bank Sta=524,539
XS Rating Curve= 0 ,0
Exp/Cntr=0.3,0.1

Type RM Length L Ch R = 1 ,564     ,292.3,328.5,364.3
XS GIS Cut Line= 3
     1892735.817      340306.312     1892615.008      340220.978
     1892132.837      339898.659
#Sta/Elev= 30
       0 1612.91    29.6  1608.5    39.4  1607.4    59.2 1605.87   108.5    1603
     138 1600.23   140.4 1600.17   147.9 1599.99   155.4  1600.1   177.9 1601.14
   217.9 1603.84   237.9 1604.93   367.9 1609.33   387.9 1609.74   407.9  1609.5
   437.9 1607.63   447.9  1607.4   517.9 1607.39   527.9  1607.6   537.9 1608.64
   547.9 1610.64   567.9 1615.64   587.9 1621.53   597.9 1624.98   607.9 1628.57
   627.9 1636.69   667.9 1653.99   687.9 1662.09   707.9 1669.46   727.9 1676.09
#Mann= 3 , 0 , 0
       0     .08       0   140.4    .045       0   155.4     .08       0
Bank Sta=140.4,155.4
XS Rating Curve= 0 ,0
Exp/Cntr=0.3,0.1

Type RM Length L Ch R = 1 ,234.5   ,251.9,235.1,219.7
XS GIS Cut Line= 3
     1892721.803      339992.285     1892720.977      339848.531
     1892726.474      339442.587
#Sta/Elev= 30
       0  1606.9    19.2  1603.7    38.3 1600.24    47.9 1598.83    53.7 1598.36
    57.5 1598.05    67.1 1597.65    68.7 1597.65    95.8 1597.85   105.4 1598.39
     115 1599.58   134.2 1602.72   143.8  1604.1   153.7 1605.01   173.5 1606.48
   183.4 1607.51   213.1 1611.56   232.9 1613.93   242.8 1614.82   252.7 1615.47
   262.6 1615.88   302.2 1616.96   312.1 1617.02     322  1616.7   341.8 1615.72
   361.6 1615.23   401.2 1615.32   490.3 1614.84   529.9  1614.4   549.7 1614.48
#Mann= 3 , 0 , 0
       0      .1       0    53.7    .045       0    68.7      .1       0
Bank Sta=53.7,68.7
XS Rating Curve= 0 ,0
Exp/Cntr=0.3,0.1

Chan Stop Cuts=-1
Use User Specified Reach Order=0
Composite Channel Slope=5